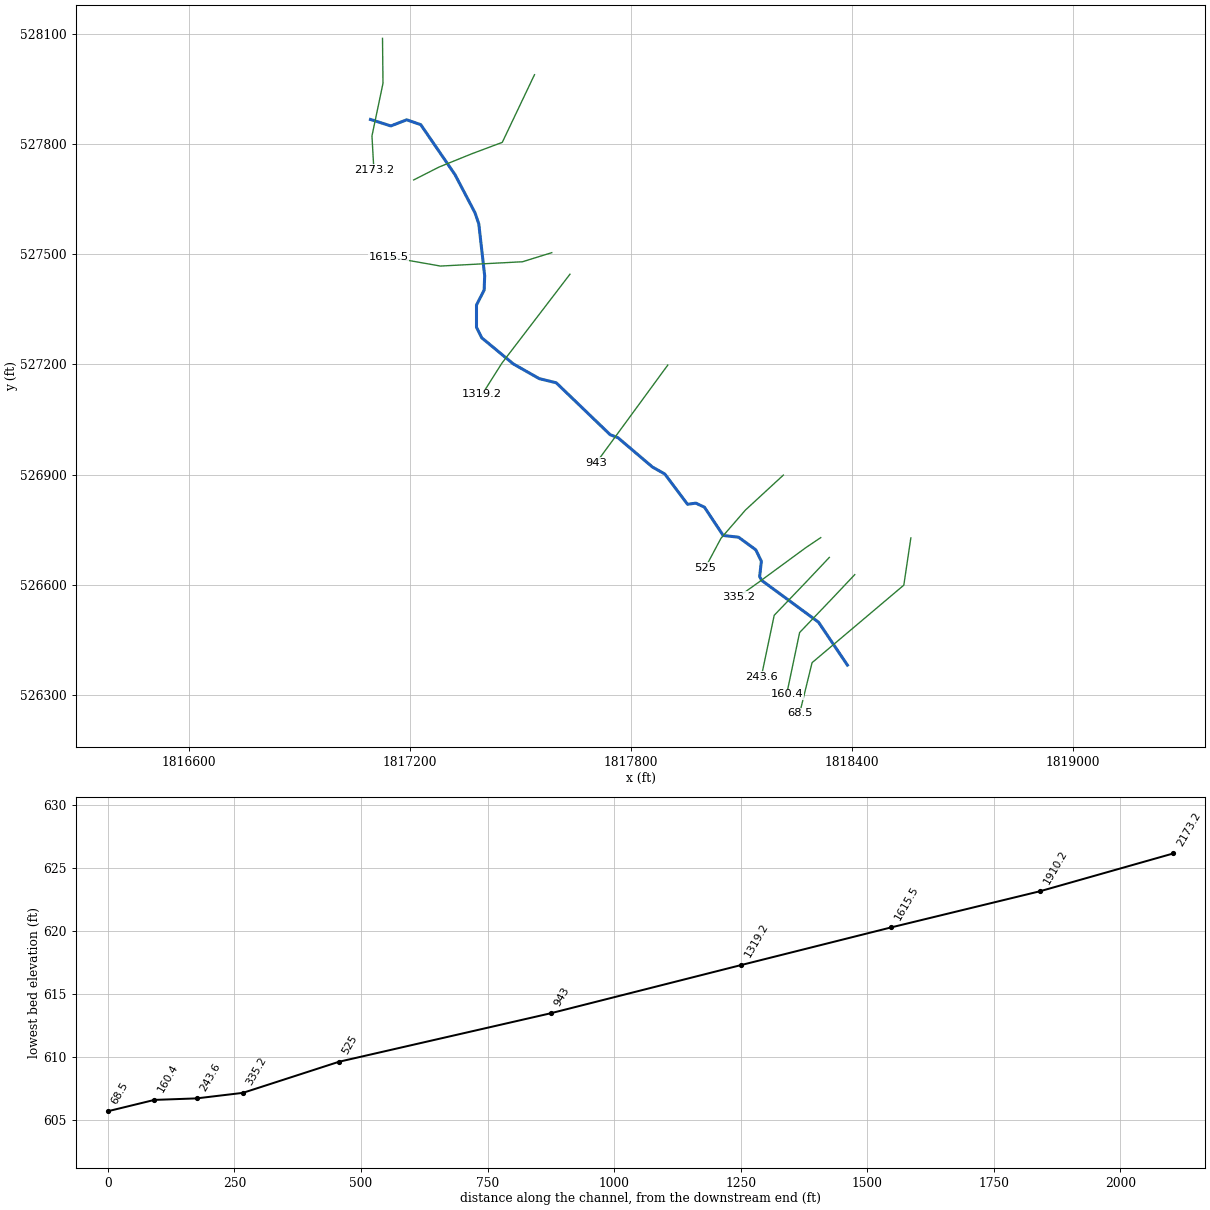
--- LICKBR2.prj (project) ---

Proj Title=LICKBR2
Current Plan=p01
Default Exp/Contr=0,0
English Units
Geom File=g01
Flow File=f01
Plan File=p01
BEGIN DESCRIPTION:
END DESCRIPTION:
DSS Export Rating Curves= 0
DSS Export Rating Curve Sorted= 0
DSS Export Volume Flow Curves= 0
DXF OffsetX= 0
DXF OffsetY= 0
DXF ScaleX= 0
DXF ScaleY= 0

--- LICKBR2.p01 (plan) ---

Plan Title=Floodplain
Program Version=4.00
Geom File=g01
Flow File=f01
K Sum by GR=0
Std Step Tol=0.01
Critical Tol=0.01
Num of Std Step Trials=20
Max Error Tol=0.3
Flow Tol Ratio=0.001
Split Flow NTrial=30
Split Flow Tol=0.02
Split Flow Ratio=0.02
Log Output Level=0
Friction Slope Method=1
Unsteady Friction Slope Method=2
Unsteady Bridges Friction Slope Method=1
Global Log Level=0
CheckData=False
Run HTab=0
Run UNet=0
Run PostProcess=0
UNET Theta=0
UNET Theta Warmup=0
UNET ZTol=0
UNET ZSATol=0
UNET MxIter=0
UNET MaxInSteps=0
UNET DtIC=0
UNET DtMin=0
UNET MaxCRTS=0
UNET WFStab=0
UNET SFStab=0
UNET WFX=0
UNET SFX=0
UNET DSS MLevel=0
UNET DZMax Abort=0
UNET Convert EG Bridges=0
UNET Use Existing IB Tables=0
UNET Froude Limit=0
UNET Froude Power=0
Write IC File=0
Echo Input=False
Echo Output=False
Write Detailed=0

--- LICKBR2.f01 (steady flow) ---

Flow Title=NFF Regression Equation
Program Version=4.10
Number of Profiles= 1
Profile Names=P100yr
River Rch & RM=LICKBR2,Main            ,2173.2
835.7206
River Rch & RM=LICKBR2,Main            ,1910.2
909.1233
Boundary for River Rch & Prof#=LICKBR2,Main            , 1
Up Type= 0
Dn Type= 3
Dn Slope=0.006
DSS Import GetInterval= 0
DSS Import GetPeak= 0
DSS Import FillOption= 0

--- LICKBR2.g01 (geometry) ---

Geom Title=USGS 10m DEM
Program Version=4.10

River Reach=LICKBR2         ,Main
Reach XY= 30
     1817092.489      527866.573     1817147.741      527848.922
     1817190.796      527865.588     1817228.991      527852.394
     1817322.046      527716.283     1817376.213      527612.811
      1817386.63      527582.255     1817402.602      527441.283
     1817401.213      527402.394      1817380.38      527361.422
      1817380.38      527301.005      1817394.67      527272.232
     1817480.608      527201.051      1817550.92      527161.121
     1817596.916      527149.877     1817743.516       527008.48
     1817764.483      527000.419      1817858.09      526920.679
     1817891.933      526901.497     1817953.546      526819.169
     1817975.942      526822.294     1817999.379      526811.357
     1818050.421      526734.273     1818092.087      526729.586
     1818138.962      526695.211     1818154.067      526663.961
     1818149.379      526622.294     1818155.108      526611.877
     1818309.275      526498.336     1818387.766      526381.428

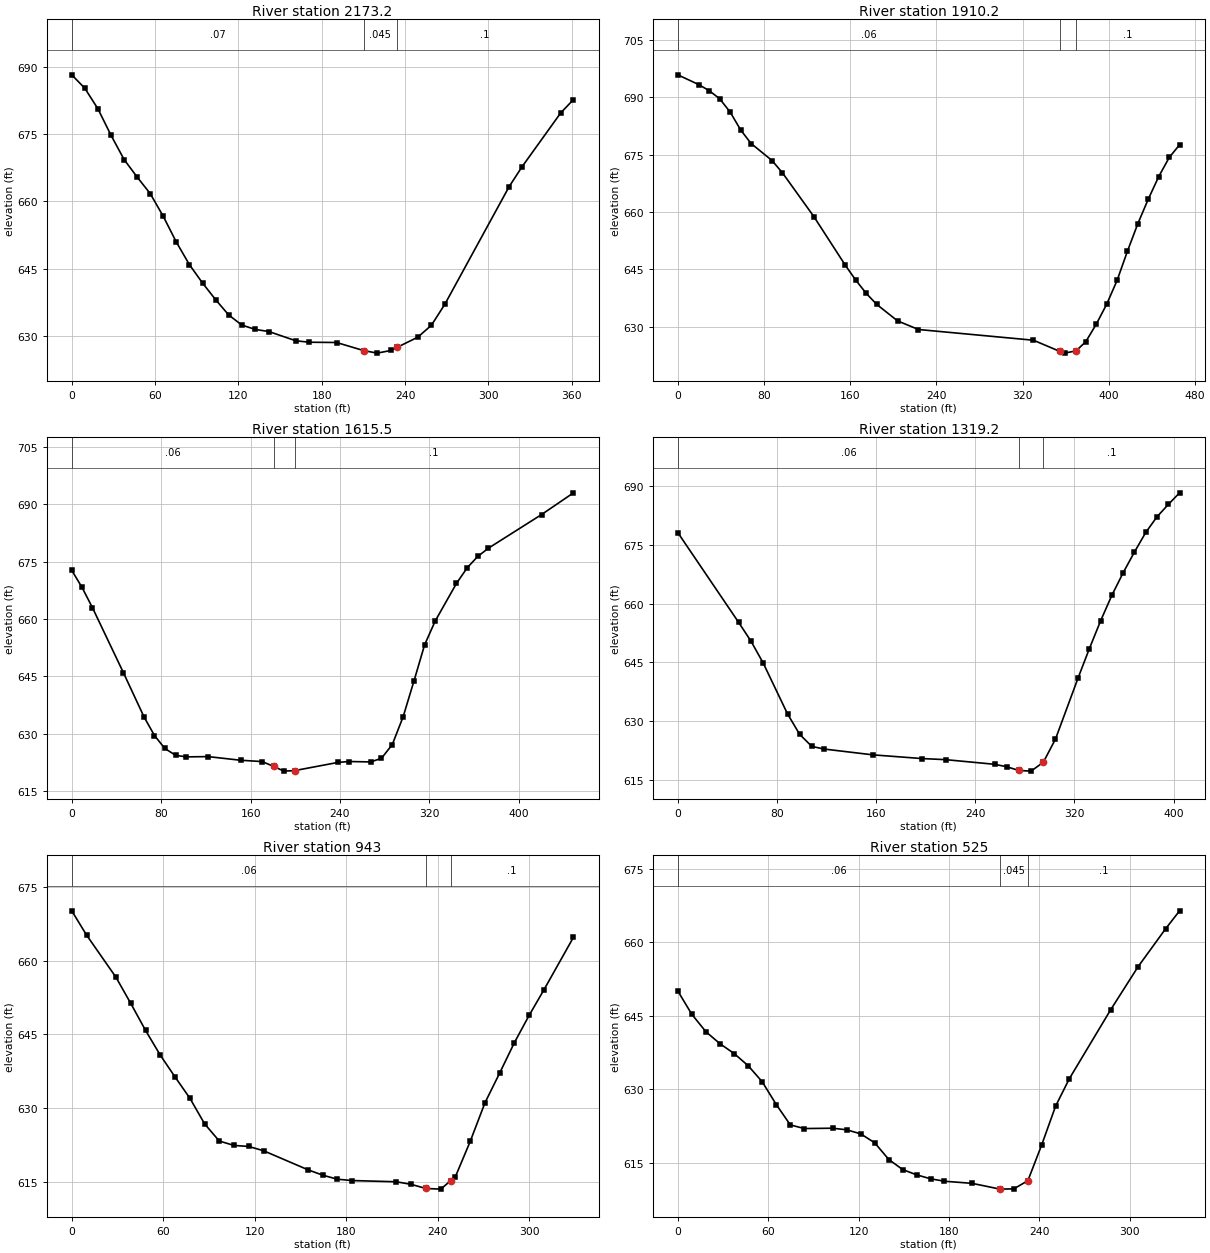
Type RM Length L Ch R = 1 ,2173.2  ,285.3,263.1,240.6
XS GIS Cut Line= 4
     1817125.139      528087.336     1817126.441       527964.94
     1817096.493      527821.711     1817101.701      527729.263
#Sta/Elev= 30
       0  688.24     9.4  685.25    18.8  680.68    28.2   674.8    37.7  669.34
    47.1  665.43    56.5  661.75    65.9  656.67    75.3  650.94    84.7  645.91
    94.2  641.79   103.6  638.08     113  634.68   122.4  632.43   132.2  631.44
   141.9  630.98   161.4  628.91   171.2  628.59   190.7  628.53   210.2  626.73
     220  626.16   229.7  626.75   234.1  627.42   249.2  629.72     259  632.38
   268.7  637.08     315  663.32   324.3  667.75   352.1  679.74   361.3  682.73
#Mann= 3 , 0 , 0
       0     .07       0   210.2    .045       0   234.1      .1       0
Bank Sta=210.2,234.1
XS Rating Curve= 0 ,0
Exp/Cntr=0.3,0.1

Type RM Length L Ch R = 1 ,1910.2  ,302.2,294.7,287.2
XS GIS Cut Line= 5
     1817537.899      527988.378     1817450.392      527804.195
     1817368.628      527773.534     1817278.785      527737.076
     1817209.774       527701.92
#Sta/Elev= 30
       0  695.84    19.4  693.29    29.1   691.7    38.8   689.6    48.6   686.1
    58.3  681.44      68   677.9    87.4  673.46    97.1  670.24   126.2  658.83
   155.4  646.12   165.1  642.22   174.8  638.78   184.5   635.9   203.9  631.58
   223.3  629.33     330  626.53   354.6   623.6   359.1  623.16   369.6  623.77
   378.5  626.12   388.2  630.67   397.9  635.89   407.6  642.14   417.2  649.76
   426.9  656.99   436.6   663.4   446.3  669.28     456  674.26   465.6  677.56
#Mann= 3 , 0 , 0
       0     .06       0   354.6    .045       0   369.6      .1       0
Bank Sta=354.6,369.6
XS Rating Curve= 0 ,0
Exp/Cntr=0.3,0.1

Type RM Length L Ch R = 1 ,1615.5  ,276.1,296.3,315.8
XS GIS Cut Line= 4
     1817584.774      527504.003     1817505.347      527479.263
     1817282.691      527467.545     1817142.066      527492.284
#Sta/Elev= 30
       0   672.7     9.2  668.23    18.5  662.96    46.2  645.99    64.7  634.41
      74  629.58    83.2  626.22    92.9  624.41   102.6     624     122  624.07
     151  623.12   170.4  622.77   180.6  621.51   189.8  620.28   199.5  620.42
   238.3  622.56     248  622.79   267.4  622.68   277.1  623.62   286.8  627.23
   296.5  634.48   306.2  643.82   315.7  653.25   325.2  659.48   344.2  669.28
   353.8  673.36   363.3  676.34   372.8  678.48   420.4  687.27   448.9  692.93
#Mann= 3 , 0 , 0
       0     .06       0   180.6    .045       0   199.5      .1       0
Bank Sta=180.6,199.5
XS Rating Curve= 0 ,0
Exp/Cntr=0.3,0.1

Type RM Length L Ch R = 1 ,1319.2  ,375,376.2,375.4
XS GIS Cut Line= 3
     1817634.253      527445.409     1817449.358      527203.222
     1817395.972      527118.586
#Sta/Elev= 27
       0  678.07    49.1  655.18      59  650.42    68.8  644.88    88.5  631.87
    98.3  626.66   108.1  623.59     118  622.92   157.3  621.44   196.6   620.5
   216.2  620.21   255.6  619.03   265.4   618.4   275.2  617.46     285  617.29
   294.9  619.56   304.7  625.47   322.9  641.02     332  648.49   341.1   655.6
   350.2  662.12   359.3  667.86   368.4  673.13   377.5  678.11   386.6  682.12
   395.7  685.25   404.8  688.22
#Mann= 3 , 0 , 0
       0     .06       0   275.2    .045       0   294.9      .1       0
Bank Sta=275.2,294.9
XS Rating Curve= 0 ,0
Exp/Cntr=0.3,0.1

Type RM Length L Ch R = 1 ,943     ,427.6,418,417.9
XS GIS Cut Line= 2
     1817899.878      527198.013     1817705.868      526932.388
#Sta/Elev= 30
       0  670.22     9.7  665.28      29  656.66    38.7  651.33    48.4  645.82
      58   640.8    67.7  636.34    77.4  632.02    87.1  626.77    96.7  623.27
   106.4  622.37   116.1  622.16   125.8  621.28   154.8  617.41   164.5  616.31
   174.1  615.48   183.8  615.21   212.8  614.96   222.5  614.43   232.2  613.59
   241.9  613.46   248.4  615.18   251.5     616   261.2  623.19   270.9  631.09
   280.6  637.19   290.2  643.36   299.9  648.94   309.6  654.15   328.9  664.83
#Mann= 3 , 0 , 0
       0     .06       0   232.2    .045       0   248.4      .1       0
Bank Sta=232.2,248.4
XS Rating Curve= 0 ,0
Exp/Cntr=0.3,0.1

Type RM Length L Ch R = 1 ,525     ,193.1,189.8,182.4
XS GIS Cut Line= 4
      1818213.68      526898.534     1818110.816      526803.482
      1818044.41      526726.659     1818001.441       526645.93
#Sta/Elev= 30
       0  650.06     9.3   645.3    18.7  641.73      28   639.3    37.4  637.29
    46.7  634.81      56  631.54    65.4  626.86    74.7  622.72      84  621.98
   102.7  622.05     112  621.73   121.4   620.9   130.7  619.07   140.1  615.65
   149.3   613.6   158.5  612.53   167.8  611.72     177  611.22   195.4  610.79
   213.9  609.61   223.1  609.67   232.4  611.34   241.6  618.67   250.8  626.56
   259.9  632.15   287.3  646.21   305.6  655.05   323.9   662.8   333.1  666.44
#Mann= 3 , 0 , 0
       0     .06       0   213.9    .045       0   232.4      .1       0
Bank Sta=213.9,232.4
XS Rating Curve= 0 ,0
Exp/Cntr=0.3,0.1

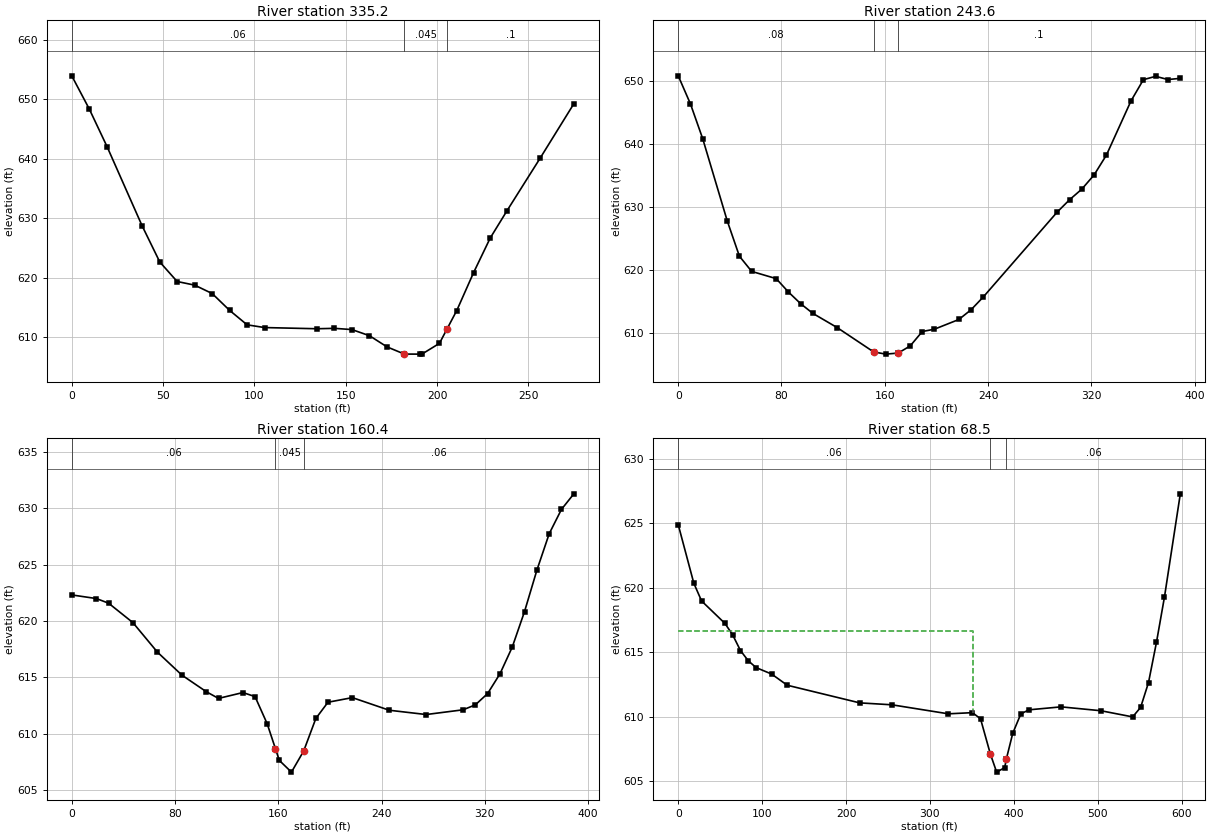
Type RM Length L Ch R = 1 ,335.2   ,87.4,91.6,95.5
XS GIS Cut Line= 4
     1818315.243      526728.395     1818275.312      526701.485
     1818144.236      526605.131     1818092.153      526567.805
#Sta/Elev= 27
       0  653.97     9.6  648.38    19.3  642.07    38.5  628.74    48.2  622.64
    57.7  619.36    67.3  618.75    76.9  617.33    86.4  614.51      96  612.07
   105.6  611.61   134.3  611.41   143.8  611.48   153.4  611.27     163  610.24
   172.6  608.36   182.1  607.15   190.4  607.14   191.7  607.14   201.3  608.95
   205.4  611.34   210.8  614.48     220  620.85   229.1  626.67   238.3  631.27
   256.6  640.19   274.9  649.27
#Mann= 3 , 0 , 0
       0     .06       0   182.1    .045       0   205.4      .1       0
Bank Sta=182.1,205.4
XS Rating Curve= 0 ,0
Exp/Cntr=0.3,0.1

Type RM Length L Ch R = 1 ,243.6   ,83.4,83.2,83.3
XS GIS Cut Line= 4
      1818338.68      526674.576     1818273.576      526605.565
     1818188.941      526517.024     1818153.785      526349.055
#Sta/Elev= 30
       0   650.9     9.5  646.42      19  640.89      38  627.84    47.4  622.25
    56.9  619.84    75.9  618.69    85.4  616.56    94.9   614.7   104.3  613.17
   123.1  610.92   151.4  607.05   160.8   606.7   170.4  606.87   179.7     608
   189.1  610.29   198.5  610.66   217.4   612.2   226.9  613.75   236.4  615.79
   293.6  629.26   303.2  631.22   312.7  632.91   322.2  635.16   331.8  638.33
   350.8  646.92   360.4  650.29   369.9  650.82   379.4  650.31     389   650.5
#Mann= 3 , 0 , 0
       0     .08       0   151.4    .045       0   170.4      .1       0
Bank Sta=151.4,170.4
XS Rating Curve= 0 ,0
Exp/Cntr=0.3,0.1

Type RM Length L Ch R = 1 ,160.4   ,94.1,91.9,89.5
XS GIS Cut Line= 4
     1818407.691      526627.701     1818342.587       526558.69
     1818257.951      526470.149     1818222.795       526302.18
#Sta/Elev= 30
       0   622.3      19  621.98    28.5  621.57    47.4  619.84    66.4  617.22
    85.4  615.18   104.3  613.71   113.7  613.12   132.6  613.64     142  613.28
   151.4  610.87   157.8  608.66   160.8  607.62   170.2  606.58   179.7  608.46
   189.1  611.34   198.5  612.78   217.4  613.19     246  612.07   274.6  611.69
   303.2  612.11   312.7  612.55   322.2  613.55   331.8  615.31   341.3  617.68
   350.8  620.83   360.4  624.51   369.9  627.73   379.4  629.89     389  631.27
#Mann= 3 , 0 , 0
       0     .06       0   157.8    .045       0   179.7     .06       0
Bank Sta=157.8,179.7
XS Rating Curve= 0 ,0
Exp/Cntr=0.3,0.1

Type RM Length L Ch R = 1 ,68.5    ,67.9,68.5,69.2
XS GIS Cut Line= 4
     1818560.035      526727.527     1818540.937      526599.055
     1818291.805      526388.117     1818257.951      526250.097
#Sta/Elev= 30
       0   624.9    18.6  620.35    27.8  618.98    55.7  617.23    64.9  616.34
    74.2  615.12    83.5  614.33    92.8   613.8   111.3   613.3   129.9  612.43
   216.3  611.06   254.7  610.91   321.9  610.21   350.7   610.3   360.3  609.82
     372  607.09   379.5  605.68   389.1  606.03  391.14  606.72   398.7   608.7
   408.3   610.2   417.9  610.52   456.3  610.75   503.7  610.45   541.6  609.97
   551.1  610.71   560.5  612.64     570  615.77   579.5  619.28   598.4   627.3
#Mann= 3 , 0 , 0
       0     .06       0     372    .045       0  391.14     .06       0
#XS Ineff= 2 , 0
          351.28  616.64
Permanent Ineff=
       F       F
Bank Sta=372,391.14
XS Rating Curve= 0 ,0
Exp/Cntr=0.3,0.1

Chan Stop Cuts=-1
Use User Specified Reach Order=0
Composite Channel Slope=5